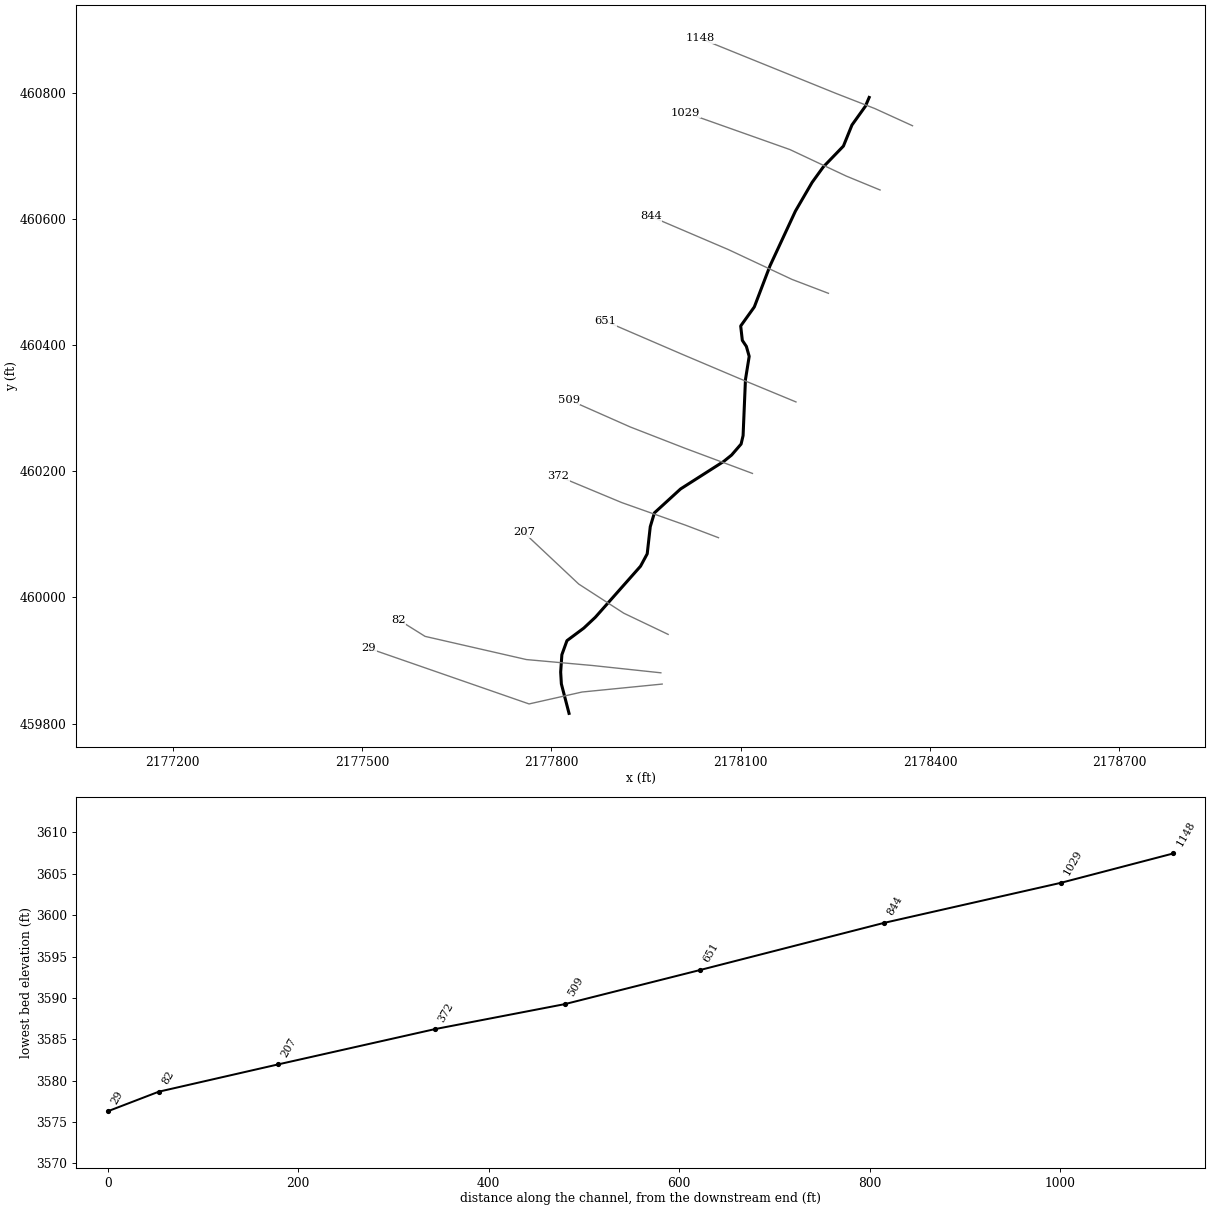
--- LFNFCRNBRYRV.prj (project) ---

Proj Title=LFNFCRNBRYRV
Current Plan=p01
Default Exp/Contr=0,0
English Units
Geom File=g01
Flow File=f01
Plan File=p01
Background Map Layer=Inundation Boundary (01pct Value_0)
BEGIN DESCRIPTION:
----------MODEL BY WOOD PLC 2021----------
Stream Name: Left Fork North Fork Cranberry River
Flood Zone: Approximate
Pocahontas County, WV
HEC-RAS Version: RAS 6.1
Vertical Datum: NAVD88
Projection: NAD 1983 StatePlane West Virginia S FIPS 4702 (US Feet)
Terrain: 1-meter LIDAR (FEMA Region III 3DEP collected 2016-2018)
Land Use: 2019 NLCD
Hydrologic Method:
WV 2010 Regional Regression Equations
Model Notes:
Model snaps to NFCRNBRYRV at the downstream
END DESCRIPTION:
DSS Export Rating Curves= 0
DSS Export Rating Curve Sorted= 0
DSS Export Volume Flow Curves= 0
DXF OffsetX= 0
DXF OffsetY= 0
DXF ScaleX= 0
DXF ScaleY= 0

--- LFNFCRNBRYRV.p01 (plan) ---

Plan Title=Floodplain
Program Version=6.00
Short Identifier=Floodplain
Geom File=g01
Flow File=f01
Subcritical Flow
K Sum by GR= 0
Std Step Tol= 0.01
Critical Tol= 0.01
Num of Std Step Trials= 20
Max Error Tol= 0.3
Flow Tol Ratio= 0.001
Split Flow NTrial= 30
Split Flow Tol= 0.02
Split Flow Ratio= 0.02
Log Output Level= 0
Friction Slope Method= 1
Unsteady Friction Slope Method= 2
Unsteady Bridges Friction Slope Method= 1
Parabolic Critical Depth
Global Vel Dist= 0 , 0 , 0
Global Log Level= 0
CheckData=True
Encroach Param=-1 ,0,0, 0
Mapping Interval=1HOUR
Computation Time Step Use Courant=        0
Computation Time Step Use Time Series=    0
Computation Time Step Count To Double=0
Computation Time Step Max Doubling=0
Computation Time Step Max Halving=0
Computation Time Step Residence Courant=0
Run HTab= 0
Run UNet= 0
Run Sediment= 0
Run PostProcess= 0
Run WQNet= 0
Run RASMapper=-1
UNET Theta= 0
UNET Theta Warmup= 0
UNET ZTol= 0
UNET ZSATol= 0
UNET MxIter= 0
UNET Max Iter WO Improvement= 0
UNET MaxInSteps= 0
UNET DtIC= 0
UNET DtMin= 0
UNET MaxCRTS= 0
UNET WFStab= 0
UNET SFStab= 0
UNET WFX= 1
UNET SFX= 1
UNET Gravity=32.174
UNET 1D Methodology=Finite Difference
UNET DSS MLevel= 1
UNET Pardiso=0
UNET DZMax Abort= 0
UNET Use Existing IB Tables= 0
UNET Froude Reduction=False
UNET Froude Limit= 0
UNET Froude Power= 0
UNET D1 Cores= 0
UNET WindReference=Eulerian
UNET WindDragFormulation=Hsu (1988)
UNET D2 Coriolis=0
UNET D2 Cores= 0
UNET D2 Theta= 1
UNET D2 Theta Warmup= 1
UNET D2 Z Tol= 0.01
UNET D2 Volume Tol= 0.01
UNET D2 Max Iterations= 20
UNET D2 Equation= 0
UNET D2 RampUpFraction=0.1
UNET D2 TimeSlices= 1
UNET D2 Turbulence Formulation=Non-Conservative (original)
UNET D2 Eddy Viscosity=0.3
UNET D2 Transverse Eddy Viscosity=0.1
UNET D2 Smagorinsky Mixing=0
UNET D2 BCVolumeCheck=0
UNET D2 Cores=0
UNET D2 SolverType=PARDISO (Direct)
UNET D2 Minimum Iterations= 2147483647
UNET D2 Maximum Iterations= 2147483647
UNET D2 Restart Number= 10
UNET D2 Relaxation Coeff=1.3
UNET D2 SOR Precondition Iterations= 10
UNET D2 ILUT Maximum Fill= 8
UNET D2 ILUT Tolerance=1E-08
UNET D1D2 MaxIter= 0
UNET D1D2 ZTol=0.01
UNET D1D2 QTol=0.1
UNET D1D2 MinQTol=1
Write IC File= 0
Write IC File at Fixed DateTime=0
Write IC File at Sim End=0
Echo Input=False
Echo Parameters=False
Echo Output=False
Write Detailed= 0
HDF Write Warmup=0
HDF Write Time Slices=0
HDF Flush=0
HDF Compression= 1
HDF Chunk Size= 1
HDF Spatial Parts= 1
HDF Use Max Rows=0
HDF Fixed Rows= 1
Calibration Method= 0
Calibration Iterations= 20
Calibration Max Change=0.05
Calibration Tolerance=0.2
Calibration Maximum=1.5
Calibration Minimum=0.5
Calibration Optimization Method= 1
WQ AD Non Conservative
WQ ULTIMATE=-1
WQ Max Comp Step=1HOUR
WQ Output Interval=15MIN
WQ Output Selected Increments= 0
WQ Output face flow=0
WQ Output face velocity=0
WQ Output face area=0
WQ Output face dispersion=0
WQ Output cell volume=0
WQ Output cell surface area=0
WQ Output cell continuity=0
WQ Output cumulative cell continuity=0
WQ Output face conc=0
WQ Output face dconc_dx=0
WQ Output face courant=0
WQ Output face peclet=0
WQ Output face adv mass=0
WQ Output face disp mass=0
WQ Output cell mass=0
WQ Output cell source sink temp=0
WQ Output nsm pathways=0
WQ Output nsm derived pathways=0
WQ Create Restart=0
WQ Fixed Restart=0
WQ System Summary=0
WQ Write To DSS=0
Sorting and Armoring Iterations= 10
XS Update Threshold= 0.02
Bed Roughness Predictor= 0
Hydraulics Update Threshold= 0.02
Energy Slope Method= 1
Volume Change Method= 1
Sediment Retention Method= 0
Sediment TS Multiplier= 1
Warm Up Method= 0
XS Weighting Method= 0
Number of US Weighted Cross Sections= 1
Number of DS Weighted Cross Sections= 1
Upstream XS Weight=0
Main XS Weight=1
Downstream XS Weight=0
Number of DS XS's Weighted with US Boundary= 1
Upstream Boundary Weight= 1
Weight of XSs Associated with US Boundary= 0
Number of US XS's Weighted with DS Boundary= 1
Downstream Boundary Weight= 0.5
Weight of XSs Associated with DS Boundary= 0.5
Percentile Method= 0
Sediment Output Level= 3
Mass or Volume Output= 0
Output Increment Type= 1
Profile and TS Output Increment= 1
Transport Output Increment 1
XS Output Flag= 0
XS Output Increment= 10
Read HDF5 Sediment Hotstart= 0
Sediment Hotstart Type= 0
Write Gradation File= 0
Read Gradation Hotstart= 0
Write HDF5 File= 1
Write Binary Output= 1
Write DSS Sediment File= 0
DSS Sediment Output Type= 1
SV Curve= 0
Specific Gage Flag= 0
Subcell Erosion Methods= 0
Subcell Deposition Methods= 0
Advection Scheme= 1
Matrix Solver= 0
Implicit Weighting Factor= 1
Maximum Outer Loop Convergence Iterations= 5
Convergence Maximum Absolute= 0.001
Convergence RMSE= 0.0001
Grain Fractions Max Abs Error= 0.001
Max Subgrid Regions= 1
Max Subgrid Length Scale= 3.402823E+38
Initial Layer Thickness= 3.402823E+38
Min Layer Thickness= 3.402823E+38
Max Layer Thickness= 3.402823E+38
Number of Layers= 5

--- LFNFCRNBRYRV.f01 (steady flow) ---

Flow Title=Flow
Program Version=6.00
Number of Profiles= 6
Profile Names=01pct,10pct,04pct,02pct,0_2pct,01plus
River Rch & RM=LFNFCRNBRYRV,Main            ,1148
     468     245     327     395     656     691
Boundary for River Rch & Prof#=LFNFCRNBRYRV,Main            , 1
Up Type= 0
Dn Type= 3
Dn Slope=0.04467
Boundary for River Rch & Prof#=LFNFCRNBRYRV,Main            , 2
Up Type= 0
Dn Type= 3
Dn Slope=0.04467
Boundary for River Rch & Prof#=LFNFCRNBRYRV,Main            , 3
Up Type= 0
Dn Type= 3
Dn Slope=0.04467
Boundary for River Rch & Prof#=LFNFCRNBRYRV,Main            , 4
Up Type= 0
Dn Type= 3
Dn Slope=0.04467
Boundary for River Rch & Prof#=LFNFCRNBRYRV,Main            , 5
Up Type= 0
Dn Type= 3
Dn Slope=0.04467
Boundary for River Rch & Prof#=LFNFCRNBRYRV,Main            , 6
Up Type= 0
Dn Type= 3
Dn Slope=0.04467
DSS Import GetInterval= 0
DSS Import GetPeak= 0
DSS Import FillOption= 0

--- LFNFCRNBRYRV.g01 (geometry) ---

Geom Title=Geometry
Program Version=6.10

River Reach=LFNFCRNBRYRV    ,Main
Reach XY= 30
     2178303.529        460792.2     2178297.618      460778.382
     2178276.264      460748.504      2178262.72       460715.13
      2178230.82      460682.075     2178213.103      460657.568
     2178186.717      460612.181     2178146.482      460525.596
     2178121.563      460460.2772178099.97386467460430.100365696
2178102.55238349460407.3234494422178108.96593717460397.738175761
2178113.43946296460381.9680143682178107.51635969460345.080497909
2178103.76790449 460256.402325342178100.62384862460243.040087889
2178085.49307974460225.5512771062178073.11335975460215.529599018
2178004.73014456460171.9058238082177963.26790776460133.980649864
     2177956.691      460112.042     2177951.863      460069.104
     2177941.289      460049.492     2177869.683      459968.596
     2177851.339      459951.371     2177824.691      459931.517
     2177816.635      459909.235     2177814.729      459881.672
     2177815.856      459862.951     2177827.985      459816.299

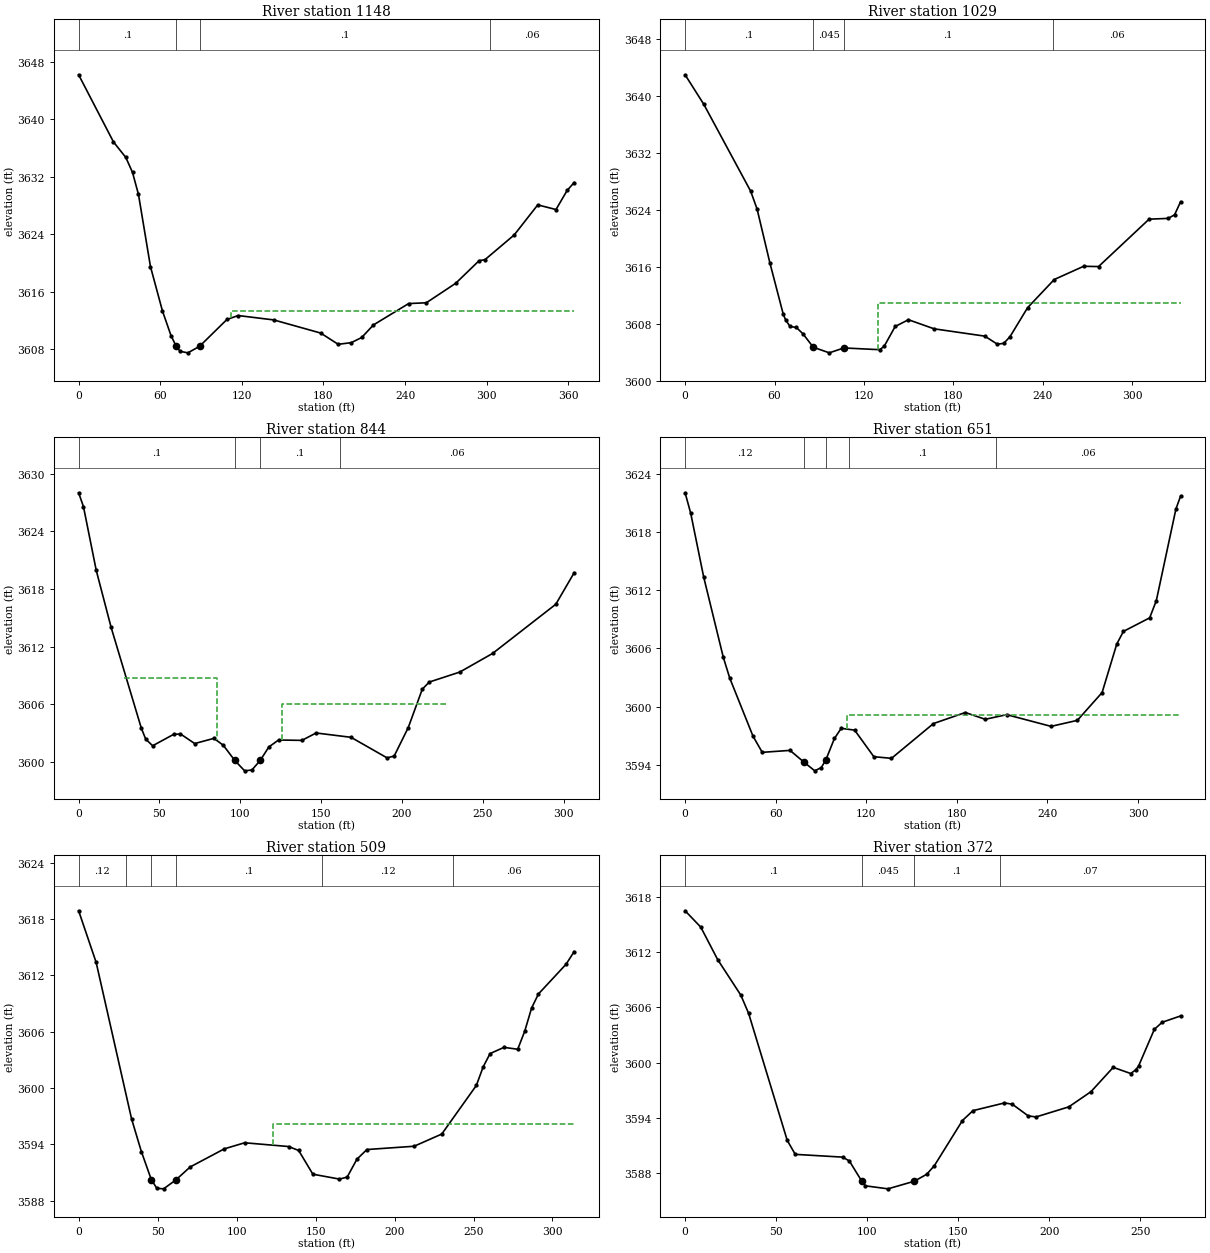
Type RM Length L Ch R = 1 ,1148    ,117.9,118.4,117.9
XS GIS Cut Line= 4
2178372.24723407460747.3435576292178312.43394697460774.626811392
2178250.52194805460798.7619974142178035.40398568460885.858538274
#Sta/Elev= 30
       0 3646.23    25.6 3636.87    34.7  3634.7    39.6 3632.62      44 3629.54
    52.8 3619.49    61.6 3613.31    67.9 3609.87   71.713608.369    74.6 3607.67
    80.3 3607.46    88.93608.369     109 3612.11   117.3 3612.66   143.4 3612.05
   177.9 3610.22   190.8 3608.65   200.4 3608.88   208.1  3609.6   216.7 3611.35
   242.6 3614.33   255.6 3614.44   277.2 3617.16   294.4 3620.31   298.7 3620.45
   320.2  3623.9   337.5 3628.09   350.9 3627.44   359.1  3630.1364.2729 3631.21
#Mann= 4 ,-1,0
       0      .1       0   71.71    .045       0    88.9      .1       0
  302.19     .06       0
#XS Ineff= 2 , 0
                          112.21         3613.26
Permanent Ineff=
       F       F
Bank Sta=71.71,88.9
XS Rating Curve= 0 ,0
Exp/Cntr(USF)=0,0
Exp/Cntr=0.3,0.1

Type RM Length L Ch R = 1 ,1029    ,185.7,185.7,185.4
XS GIS Cut Line= 4
2178320.82879429460645.5560339732178267.31164267460667.592508166
2178178.11638998460709.5667447262178012.31815558460768.330675908
#Sta/Elev= 30
       0 3643.03    12.5 3638.89      44 3626.64    48.3 3624.12    56.9 3616.53
    65.8 3609.36    67.4 3608.54    70.4 3607.61    74.6 3607.47      79 3606.59
   85.993604.689    96.7  3603.9   106.5 3604.59   130.6 3604.34   133.6 3604.85
   140.9 3607.61   149.8 3608.56     167 3607.28     201 3606.25   209.4 3605.12
   213.7 3605.23   217.9 3606.17   229.7 3610.25   247.6 3614.22   267.3 3616.08
   277.3 3616.04   311.2 3622.71     324 3622.82   328.3 3623.33332.3587 3625.17
#Mann= 4 ,-1,0
       0      .1       0   85.99    .045       0   106.5      .1       0
  246.45     .06       0
#XS Ineff= 2 , 0
                          129.65         3610.85
Permanent Ineff=
       F       F
Bank Sta=85.99,106.5
XS Rating Curve= 0 ,0
Exp/Cntr(USF)=0,0
Exp/Cntr=0.3,0.1

Type RM Length L Ch R = 1 ,844     ,191.5,193,193
XS GIS Cut Line= 4
2178238.97903299460481.8565113922178181.26445773460503.892985586
2178080.52628998460551.1140017152177957.75164805460603.581797414
#Sta/Elev= 30
       0    3628       3 3626.55    10.9 3619.92    20.1 3613.99    38.8 3603.49
    41.5 3602.36    45.8 3601.67    58.7 3602.85      63  3602.9    71.8  3601.9
    83.7 3602.44    89.5 3601.72   96.583600.145   102.7 3599.06   107.2 3599.15
  112.323600.143   117.7 3601.55   123.7 3602.27   138.1 3602.23   146.9    3603
   168.5 3602.55   190.8 3600.41   195.2  3600.6   203.9 3603.56   212.6 3607.56
   216.9  3608.3   235.8 3609.34   256.1 3611.28   295.2  3616.4306.5508 3619.68
#Mann= 4 ,-1,0
       0      .1       0   96.58    .045       0  112.32      .1       0
  161.78     .06       0
#XS Ineff= 2 ,-1
   27.91   85.47 3608.74  125.59  227.91 3606.01
Permanent Ineff=
       F       F
Bank Sta=96.58,112.32
XS Rating Curve= 0 ,0
Exp/Cntr(USF)=0,0
Exp/Cntr=0.3,0.1

Type RM Length L Ch R = 1 ,651     ,139.6,142,142.4
XS GIS Cut Line= 4
2178187.56059321460309.7621414992178096.26662869460347.538954403
2178007.07137601460385.3157673062177885.34608998460437.783563005
#Sta/Elev= 30
       0 3622.07     3.7 3619.97    12.3 3613.38    25.3 3605.09    29.6 3602.93
      45 3596.94    51.1 3595.28    69.5 3595.48    78.7 3594.27    85.9 3593.37
    90.2 3593.71    93.23594.489    98.9 3596.71   103.4 3597.76   112.3 3597.57
     125 3594.83   136.7 3594.66   164.5 3598.25   185.6 3599.39   198.8 3598.69
     213 3599.17   242.4 3597.96   259.8 3598.58   276.2 3601.45   285.9 3606.45
   290.3 3607.76   307.7 3609.16   312.1 3610.93   325.1  3620.4 328.218 3621.74
#Mann= 5 ,-1,0
       0     .12       0    78.7    .045       0    93.2     .12       0
   108.8      .1       0  205.67     .06       0
#XS Ineff= 2 , 0
                          107.07          3599.1
Permanent Ineff=
       F       F
Bank Sta=78.7,93.2
XS Rating Curve= 0 ,0
Exp/Cntr(USF)=0,0
Exp/Cntr=0.3,0.1

Type RM Length L Ch R = 1 ,509     ,132.5,136.8,139.7
XS GIS Cut Line= 4
2178118.59802932460196.4854420962178011.43929401460236.470044823
2177925.07255212460270.0571111152177827.51012146 460313.24048206
#Sta/Elev= 30
       0 3618.89    11.1 3613.38    33.5 3596.72    39.7 3593.23      46 3590.24
    49.5 3589.31    53.8 3589.25    61.5 3590.19    70.6 3591.58    92.2 3593.51
   105.1 3594.16   132.9 3593.76   139.3 3593.34   148.3 3590.81   165.1 3590.29
     170  3590.5   176.2 3592.41   182.5 3593.44   212.4 3593.79   229.9 3595.09
   251.8 3600.27   256.1 3602.24   260.5 3603.67   269.3 3604.33     278 3604.13
   282.4 3606.04   286.8 3608.53   291.1 3610.02   308.6 3613.19313.7355 3614.54
#Mann= 6 ,-1,0
       0     .12       0      30      .1       0      46    .045       0
    61.5      .1       0  154.38     .12       0  237.04     .06       0
#XS Ineff= 2 , 0
                          123.04         3596.21
Permanent Ineff=
       F       F
Bank Sta=46,61.5
XS Rating Curve= 0 ,0
Exp/Cntr(USF)=0,0
Exp/Cntr=0.3,0.1

Type RM Length L Ch R = 1 ,372     ,168.4,164.5,157.8
XS GIS Cut Line= 4
2178064.78595127460094.6441791342178012.31815558460114.581941499
2177911.57998783460150.2600425752177810.84182009460192.234279134
#Sta/Elev= 30
       0 3616.55     8.6 3614.77    17.9 3611.22    30.6 3607.35    34.9 3605.35
    56.1  3591.5    60.5 3589.98    86.5 3589.68    90.2 3589.26   97.043587.049
      99 3586.55   111.4 3586.22  125.863587.049   132.7 3587.81   136.9 3588.75
   152.3 3593.67   158.1 3594.75   175.4 3595.59   179.7 3595.45   188.4 3594.18
   192.7 3594.06   210.7 3595.16   222.9 3596.82   235.1 3599.47   244.7  3598.8
   247.4 3599.19     249  3599.6   257.7 3603.62     262 3604.39272.1309 3605.08
#Mann= 4 ,-1,0
       0      .1       0   97.04    .045       0  125.86      .1       0
     173     .07       0
Bank Sta=97.04,125.86
XS Rating Curve= 0 ,0
Exp/Cntr(USF)=0,0
Exp/Cntr=0.3,0.1

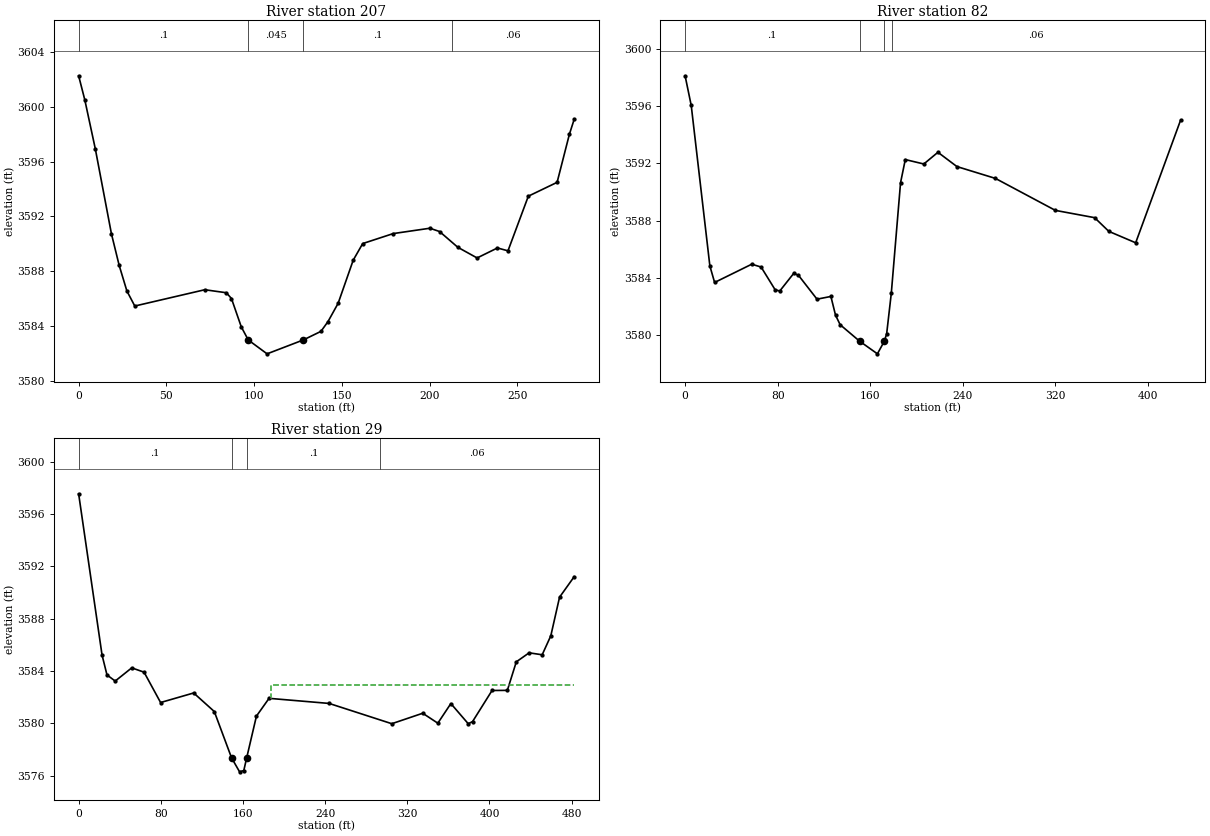
Type RM Length L Ch R = 1 ,207     ,112,125.4,131.1
XS GIS Cut Line= 4
2177985.03490181459941.4382156932177914.72805557 459975.01760494
2177843.37185342460021.1892651552177756.27531256460103.039026445
#Sta/Elev= 30
       0 3602.26     3.5 3600.51     9.5 3596.93    18.7 3590.72    23.1 3588.42
    27.5 3586.55      32 3585.45    71.9 3586.64    84.2 3586.42    87.1    3586
    92.7 3583.93   96.673582.973   107.4 3581.96  128.033582.973   138.1  3583.6
   142.1 3584.31   147.9 3585.65   156.5  3588.8   161.9 3590.01   179.3 3590.74
   200.2 3591.13   205.7 3590.89   216.1 3589.74   227.1 3588.96   238.7 3589.69
   244.7 3589.48   256.3 3593.47   272.7 3594.48   279.7 3597.99282.4263 3599.08
#Mann= 4 ,-1,0
       0      .1       0   96.67    .045       0  128.03      .1       0
  212.91     .06       0
Bank Sta=96.67,128.03
XS Rating Curve= 0 ,0
Exp/Cntr(USF)=0,0
Exp/Cntr=0.3,0.1

Type RM Length L Ch R = 1 ,82      ,46.7,53.4,57.9
XS GIS Cut Line= 5
2177973.49198676459880.5755726822177865.40832762459892.118487736
2177760.47273622459901.5626909612177599.92128138459938.290147951
2177557.94704482  459964.5240458
#Sta/Elev= 30
       0 3598.14     5.3 3596.06    21.4 3584.82    25.5 3583.66    57.6 3584.94
    65.7 3584.74    77.8 3583.15    81.8 3583.06    93.8 3584.29    97.9 3584.17
     114 3582.49     126 3582.68     130 3581.37     134  3580.7  150.733579.552
   166.2 3578.66   172.2 3579.55   174.2 3580.07   178.2  3582.9   186.2 3590.65
   190.3 3592.27   206.3 3591.96   218.5 3592.78   234.9 3591.78   268.2 3590.95
     320 3588.71   353.9  3588.2   366.2 3587.24   389.4 3586.44428.2548 3595.04
#Mann= 4 ,-1,0
       0      .1       0  150.73    .045       0   172.2      .1       0
   178.7     .06       0
Bank Sta=150.73,172.2
XS Rating Curve= 0 ,0
Exp/Cntr(USF)=0,0
Exp/Cntr=0.3,0.1

Type RM Length L Ch R = 1 ,29      ,,,
XS GIS Cut Line= 4
2177975.59069859459862.7365221442177848.61863299459850.144251176
2177764.67015988459831.2558447252177510.72602869459919.401741499
#Sta/Elev= 30
       0 3597.56    22.8 3585.23    27.6 3583.71    35.6 3583.24    51.7 3584.25
    63.7 3583.92    79.8  3581.6     112 3582.33   132.1 3580.91  148.863577.376
   156.7  3576.3   160.8  3576.4  163.633577.375   173.1 3580.56   185.4 3581.92
   243.9 3581.53   304.9 3579.98     335 3580.78   349.7 3580.02   362.4 3581.52
   379.3 3579.98   383.5 3580.14   402.5 3582.52   417.4 3582.53   426.1 3584.71
   438.6  3585.4   451.3 3585.25   459.7  3586.7   468.2 3589.65482.4493 3591.22
#Mann= 4 ,-1,0
       0      .1       0  148.86    .045       0  163.63      .1       0
  293.64     .06       0
#XS Ineff= 2 , 0
                          187.57         3582.92
Permanent Ineff=
       F       F
Bank Sta=148.86,163.63
XS Rating Curve= 0 ,0
Exp/Cntr(USF)=0,0
Exp/Cntr=0.3,0.1
LCMann Table=0

Chan Stop Cuts=-1
Use User Specified Reach Order=0
Composite Channel Slope=5